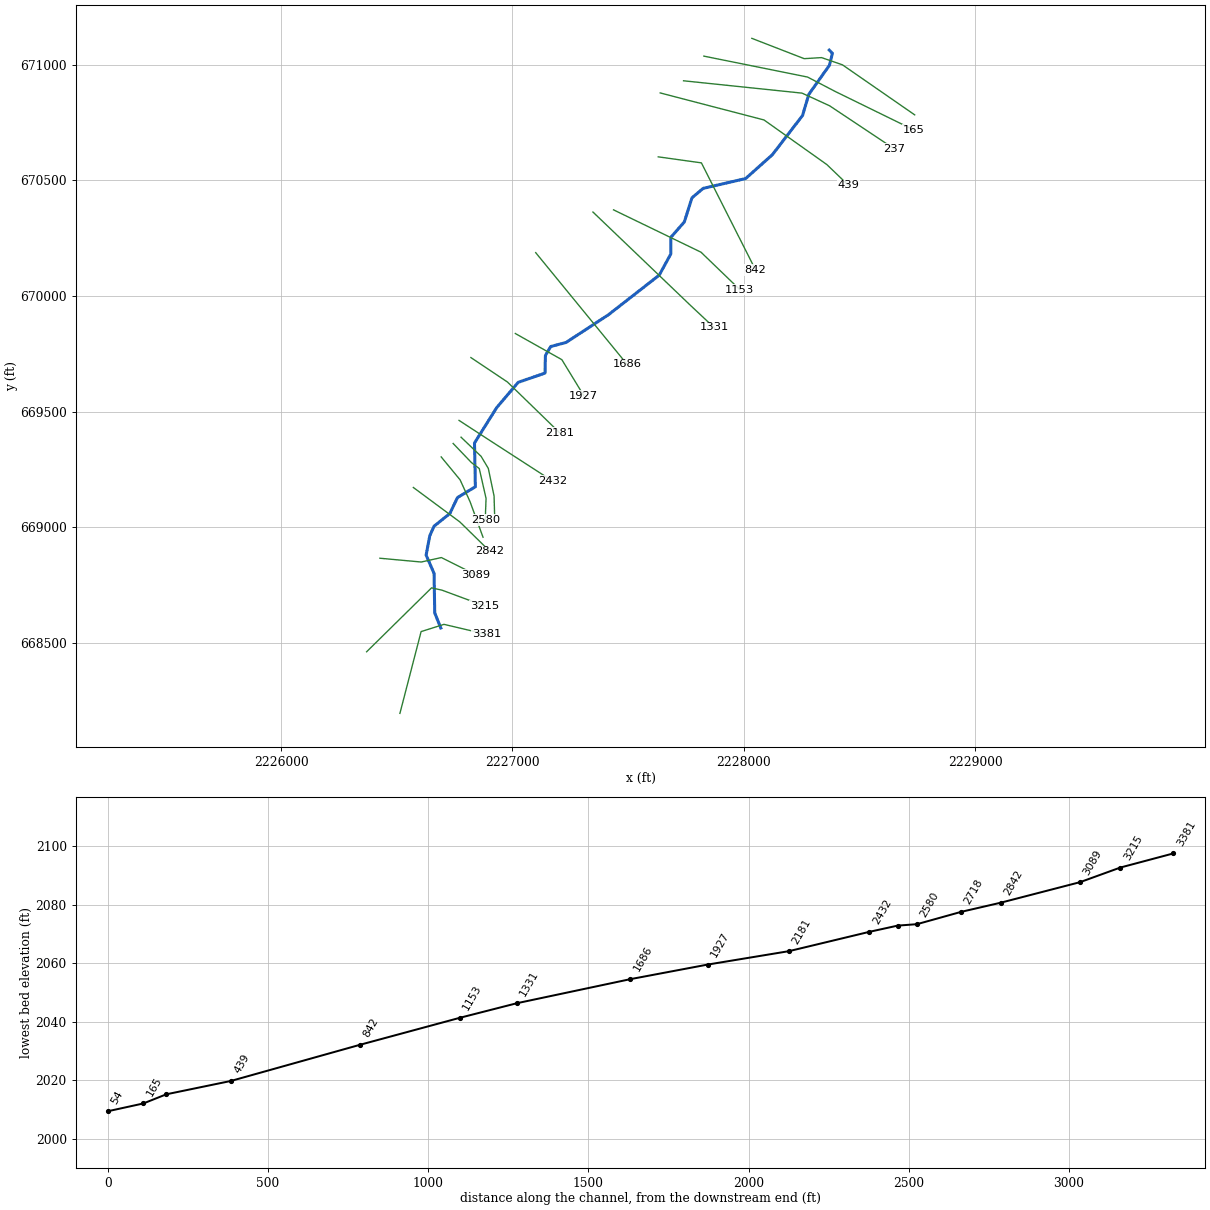
--- HIERRLKRN.prj (project) ---

Proj Title=HIERRLKRN
Current Plan=p01
Default Exp/Contr=0,0
English Units
Geom File=g01
Flow File=f01
Plan File=p01
BEGIN DESCRIPTION:
----------MODEL BY WOOD PLC 2022----------
AFH study
Randolph County, WV
HEC-RAS Version: RAS 6.2
Vertical Datum: NAVD88
Projection: NAD 1983 StatePlane West Virginia S FIPS 4702 (US Feet)
Terrain: 1-meter LIDAR (FEMA Region III 3DEP collected 2016-2018)
Land Use: 2019 NLCD
Hydrologic Method:
WV SIR2010-5033 regression equations
Additional Model Notes:
None
END DESCRIPTION:
DSS Export Rating Curves= 0
DSS Export Rating Curve Sorted= 0
DSS Export Volume Flow Curves= 0
DXF OffsetX= 0
DXF OffsetY= 0
DXF ScaleX= 0
DXF ScaleY= 0

--- HIERRLKRN.p01 (plan) ---

Plan Title=Floodplain
Program Version=6.20
Short Identifier=Floodplain
Geom File=g01
Flow File=f01
Subcritical Flow
K Sum by GR= 0
Std Step Tol= 0.01
Critical Tol= 0.01
Num of Std Step Trials= 20
Max Error Tol= 0.3
Flow Tol Ratio= 0.001
Split Flow NTrial= 30
Split Flow Tol= 0.02
Split Flow Ratio= 0.02
Log Output Level= 0
Friction Slope Method= 1
Unsteady Friction Slope Method= 2
Unsteady Bridges Friction Slope Method= 1
Parabolic Critical Depth
Global Vel Dist= 0 , 0 , 0
Global Log Level= 0
CheckData=True
Encroach Param=-1 ,0,0, 0
Mapping Interval=1HOUR
Computation Time Step Use Courant=        0
Computation Time Step Use Time Series=    0
Computation Time Step Count To Double=0
Computation Time Step Max Doubling=0
Computation Time Step Max Halving=0
Computation Time Step Residence Courant=0
Run HTab= 0
Run UNet= 0
Run Sediment= 0
Run PostProcess= 0
Run WQNet= 0
Run RASMapper=-1
UNET Theta= 0
UNET Theta Warmup= 0
UNET ZTol= 0
UNET ZSATol= 0
UNET MxIter= 0
UNET Max Iter WO Improvement= 0
UNET MaxInSteps= 0
UNET DtIC= 0
UNET DtMin= 0
UNET MaxCRTS= 0
UNET WFStab= 0
UNET SFStab= 0
UNET WFX= 1
UNET SFX= 1
UNET Gravity=32.174
UNET 1D Methodology=Finite Difference
UNET DSS MLevel= 1
UNET Pardiso=0
UNET DZMax Abort= 0
UNET Use Existing IB Tables= 0
UNET Froude Reduction=False
UNET Froude Limit= 0
UNET Froude Power= 0
UNET D1 Cores= 0
UNET WindReference=Eulerian
UNET WindDragFormulation=Hsu (1988)
UNET D2 Coriolis=0
UNET D2 Cores= 0
UNET D2 Theta= 1
UNET D2 Theta Warmup= 1
UNET D2 Z Tol= 0.01
UNET D2 Volume Tol= 0.01
UNET D2 Max Iterations= 20
UNET D2 Equation= 0
UNET D2 RampUpFraction=0.1
UNET D2 TimeSlices= 1
UNET D2 Turbulence Formulation=Non-Conservative (original)
UNET D2 Eddy Viscosity=0.3
UNET D2 Transverse Eddy Viscosity=0.1
UNET D2 Smagorinsky Mixing=0
UNET D2 BCVolumeCheck=0
UNET D2 Cores=0
UNET D2 SolverType=PARDISO (Direct)
UNET D2 Minimum Iterations= 2147483647
UNET D2 Maximum Iterations= 2147483647
UNET D2 Restart Number= 10
UNET D2 Relaxation Coeff=1.3
UNET D2 SOR Precondition Iterations= 10
UNET D2 ILUT Maximum Fill= 8
UNET D2 ILUT Tolerance=1E-08
UNET D1D2 MaxIter= 0
UNET D1D2 ZTol=0.01
UNET D1D2 QTol=0.1
UNET D1D2 MinQTol=1
Write IC File= 0
Write IC File at Fixed DateTime=0
Write IC File at Sim End=0
Echo Input=False
Echo Parameters=False
Echo Output=False
Write Detailed= 0
HDF Write Warmup=0
HDF Write Time Slices=0
HDF Flush=0
HDF Compression= 1
HDF Chunk Size= 1
HDF Spatial Parts= 1
HDF Use Max Rows=0
HDF Fixed Rows= 1
Calibration Method= 0
Calibration Iterations= 20
Calibration Max Change=0.05
Calibration Tolerance=0.2
Calibration Maximum=1.5
Calibration Minimum=0.5
Calibration Optimization Method= 1
WQ AD Non Conservative
WQ ULTIMATE=-1
WQ Max Comp Step=1HOUR
WQ Output Interval=15MIN
WQ Output Selected Increments= 0
WQ Output face flow=0
WQ Output face velocity=0
WQ Output face area=0
WQ Output face dispersion=0
WQ Output cell volume=0
WQ Output cell surface area=0
WQ Output cell continuity=0
WQ Output cumulative cell continuity=0
WQ Output face conc=0
WQ Output face dconc_dx=0
WQ Output face courant=0
WQ Output face peclet=0
WQ Output face adv mass=0
WQ Output face disp mass=0
WQ Output cell mass=0
WQ Output cell source sink temp=0
WQ Output nsm pathways=0
WQ Output nsm derived pathways=0
WQ Create Restart=0
WQ Fixed Restart=0
WQ System Summary=0
WQ Write To DSS=0
Sorting and Armoring Iterations= 10
XS Update Threshold= 0.02
Bed Roughness Predictor= 0
Hydraulics Update Threshold= 0.02
Energy Slope Method= 1
Volume Change Method= 1
Sediment Retention Method= 0
Sediment TS Multiplier= 1
Warm Up Method= 0
XS Weighting Method= 0
Number of US Weighted Cross Sections= 1
Number of DS Weighted Cross Sections= 1
Upstream XS Weight=0
Main XS Weight=1
Downstream XS Weight=0
Number of DS XS's Weighted with US Boundary= 1
Upstream Boundary Weight= 1
Weight of XSs Associated with US Boundary= 0
Number of US XS's Weighted with DS Boundary= 1
Downstream Boundary Weight= 0.5
Weight of XSs Associated with DS Boundary= 0.5
Percentile Method= 0
Sediment Output Level= 3
Mass or Volume Output= 0
Output Increment Type= 1
Profile and TS Output Increment= 1
Transport Output Increment 1
XS Output Flag= 0
XS Output Increment= 10
Read HDF5 Sediment Hotstart= 0
Sediment Hotstart Type= 0
Write Gradation File= 0
Read Gradation Hotstart= 0
Write HDF5 File= 1
Write Binary Output= 1
Write DSS Sediment File= 0
DSS Sediment Output Type= 1
SV Curve= 0
Specific Gage Flag= 0
Subcell Erosion Methods= 0
Subcell Deposition Methods= 0
Advection Scheme= 1
Matrix Solver= 0
Implicit Weighting Factor= 1
Maximum Outer Loop Convergence Iterations= 5
Convergence Maximum Absolute= 0.001
Convergence RMSE= 0.0001
Grain Fractions Max Abs Error= 0.001
Max Subgrid Regions= 1
Max Subgrid Length Scale= 3.402823E+38
Initial Layer Thickness= 3.402823E+38
Min Layer Thickness= 3.402823E+38
Max Layer Thickness= 3.402823E+38
Number of Layers= 5

--- HIERRLKRN.f01 (steady flow) ---

Flow Title=Flow
Program Version=6.20
Number of Profiles= 1
Profile Names=P100yr
River Rch & RM=HIERRLKRN,Main            ,3381
     360
Boundary for River Rch & Prof#=HIERRLKRN,Main            , 1
Up Type= 0
Dn Type= 3
Dn Slope=0.02378
DSS Import GetInterval= 0
DSS Import GetPeak= 0
DSS Import FillOption= 0

--- HIERRLKRN.g01 (geometry) ---

Geom Title=Geometry
Program Version=6.20

River Reach=HIERRLKRN       ,Main
Reach XY= 30
2226690.13568959668565.1239910132226663.99266995668630.278768599
     2226661.083668800.9850000142226626.75487204668879.899760857
      2226642.55 668963.745000022226660.99600001669004.978000015
2226729.35600001669059.8820000142226762.12500004669128.675999999
2226839.59900001669175.5510000142226835.86600001669364.613000005
2226931.56899999 669517.17400001     2227024.668669626.982999995
2227140.55400003669666.697000012     2227142.507669743.303000003
2227165.51000002669781.7140000162227231.69899999669799.292000011
2227414.64200002669918.8670000142227634.26000002670090.091000021
2227684.38999999670181.8879999972227684.60699998670253.762999997
2227742.68000005670319.9090000092227775.86213382670424.582038373
2227824.19100001670465.2210000162228007.78400001      670507.669
2228123.40899999      670610.7942228253.87800004670780.325000003
2228280.70100001670871.471000016     2228370.024670997.252000004
  2228382.918183671049.075225853     2228369.437      671062.881

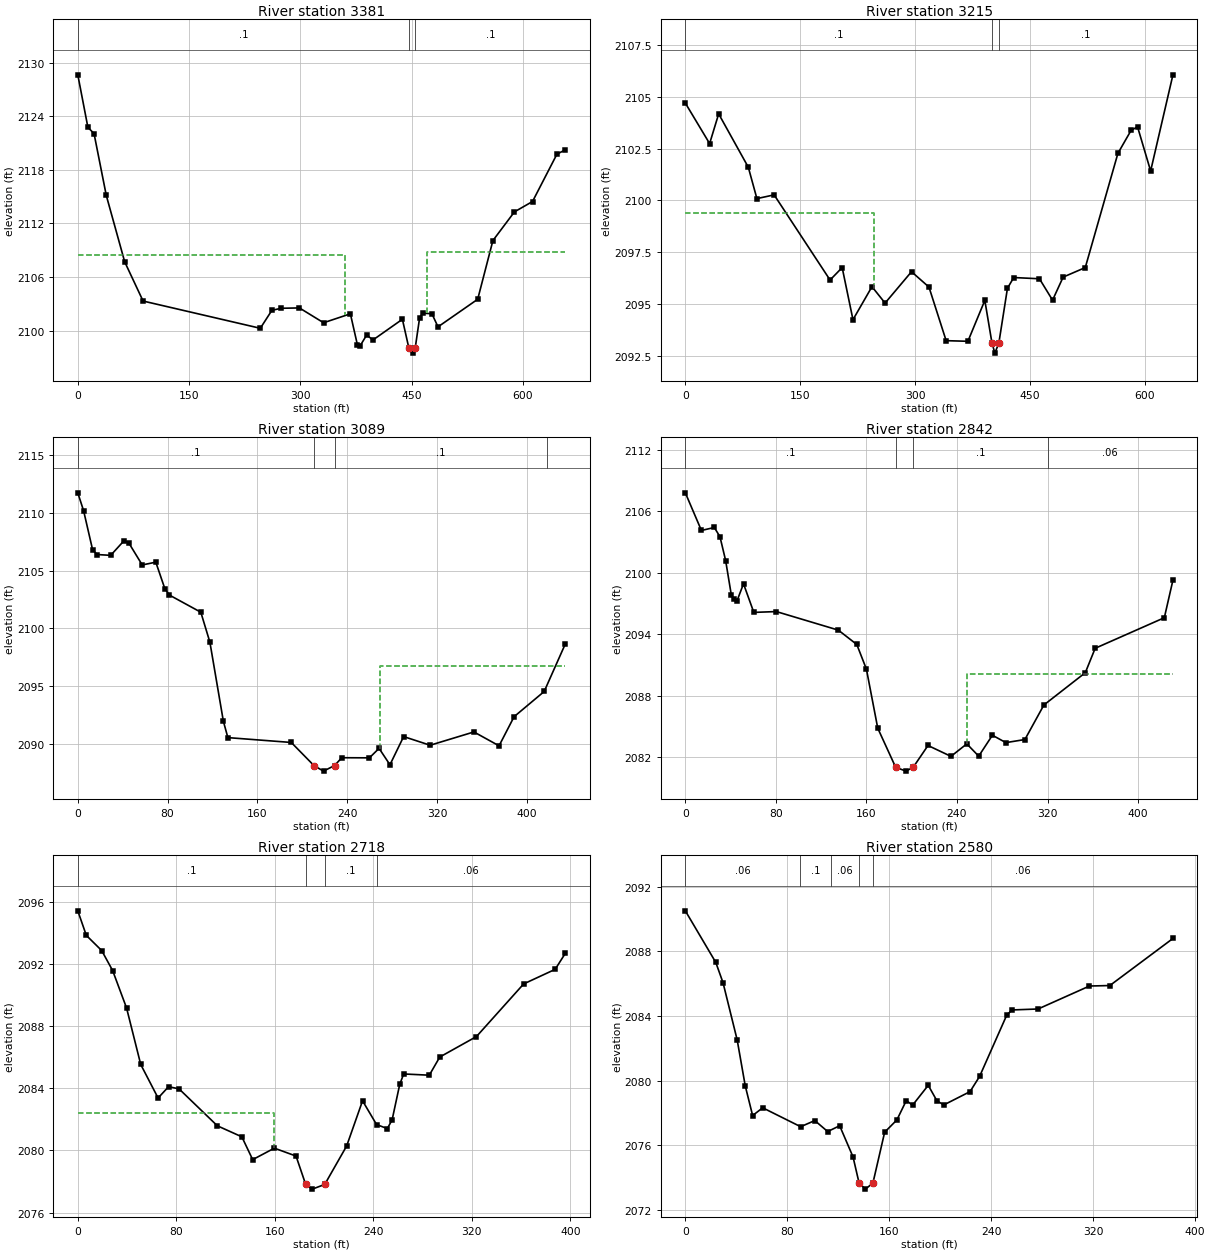
Type RM Length L Ch R = 1 ,3381    ,167.9,165.7,163.3
XS GIS Cut Line= 4
2226513.45165608668195.994090266 2226605.1048713 668549.47591076
2226703.91081132668580.8036430442226887.24561972668537.669095502
#Sta/Elev= 30
       0 2128.63    13.6 2122.76    21.9 2122.05    38.4 2115.13    63.2  2107.7
      88 2103.31     246 2100.26   261.6 2102.27     274  2102.5   298.7 2102.54
   331.3 2100.88   367.4 2101.88   376.9  2098.4   380.1 2098.24   389.4 2099.51
   397.8 2098.95   437.5 2101.27  446.14 2098.08   452.3 2097.48  454.83 2098.08
   460.7 2101.42   464.9 2101.95   477.3 2101.89   485.5 2100.42     539 2103.51
   559.5 2110.08   588.5 2113.29   612.9 2114.45   645.8 2119.75   657.2 2120.24
#Mann= 3 ,-1,0
       0      .1       0  446.14    .045       0  454.83      .1       0
#XS Ineff= 2 , 0
          360.81 2108.43  471.22         2108.75
Permanent Ineff=
       F       F
Bank Sta=446.14,454.83
XS Rating Curve= 0 ,0
Exp/Cntr(USF)=0,0
Exp/Cntr=0.3,0.1

Type RM Length L Ch R = 1 ,3215    ,123.5,125.9,128
XS GIS Cut Line= 4
2226369.59019529 668462.277267912226650.21683661668738.562605967
2226695.47389183668728.5448657782226879.47583149668660.349016301
#Sta/Elev= 30
       0 2104.69    31.7 2102.74    43.5 2104.17    82.2  2101.6    93.4 2100.09
   115.9 2100.27   188.9 2096.17   204.7 2096.77   218.8 2094.26   243.6 2095.85
   260.7 2095.06   295.2 2096.57     318 2095.83   340.4 2093.25   368.8 2093.22
   390.9 2095.19   400.2 2093.14     404 2092.65   409.22093.133   420.4 2095.77
   428.6 2096.29   462.2 2096.23   479.3  2095.2   493.1 2096.31     522 2096.77
   564.6 2102.27   581.7 2103.37   590.2 2103.55   607.3 2101.42   636.4 2106.05
#Mann= 3 ,-1,0
       0      .1       0   400.2    .045       0   409.2      .1       0
#XS Ineff= 2 , 0
          245.85 2099.41
Permanent Ineff=
       F       F
Bank Sta=400.2,409.2
XS Rating Curve= 0 ,0
Exp/Cntr(USF)=0,0
Exp/Cntr=0.3,0.1

Type RM Length L Ch R = 1 ,3089    ,251.7,247.2,236.6
XS GIS Cut Line= 4
2226427.00976047668866.5947922722226605.69138449668850.226419975
2226692.55005215668869.5251919092226841.06220035668795.350813329
#Sta/Elev= 30
       0 2111.73     5.2 2110.17    13.2  2106.8    17.2 2106.39    29.3 2106.32
    41.3  2107.6    45.4  2107.4    57.4 2105.49    69.5 2105.73    77.5 2103.45
    81.5 2102.89   109.6  2101.4   117.7  2098.8   129.7 2091.96   133.7 2090.55
   190.2 2090.13   210.4 2088.13   218.9 2087.65  228.752088.134   235.2 2088.81
   259.8  2088.8   268.4 2089.62   278.1  2088.2   290.3 2090.64   313.9 2089.89
   352.9 2091.04   375.3 2089.84   388.7 2092.36   415.5 2094.54   434.4 2098.67
#Mann= 4 ,-1,0
       0      .1       0   210.4    .045       0  228.75      .1       0
  418.41     .06       0
#XS Ineff= 2 , 0
                           268.8         2096.72
Permanent Ineff=
       F       F
Bank Sta=210.4,228.75
XS Rating Curve= 0 ,0
Exp/Cntr(USF)=0,0
Exp/Cntr=0.3,0.1

Type RM Length L Ch R = 1 ,2842    ,126.4,123.5,118.4
XS GIS Cut Line= 3
 2226571.5495453669172.4274279322226772.48212684669023.590567148
2226901.62674014668897.123193996
#Sta/Elev= 30
       0 2107.78    14.2 2104.11    25.6  2104.4    30.6  2103.5    35.6 2101.18
    40.6 2097.84    42.8 2097.38    45.6 2097.23    51.4 2098.91    60.5 2096.12
    80.4  2096.2   135.2 2094.39   151.5 2092.99     160 2090.58     170 2084.83
   185.8 2081.02   194.9 2080.64  201.312081.011   214.4 2083.14   234.7 2082.08
   248.7  2083.3   259.2  2082.1   271.3 2084.14   283.2 2083.42     300 2083.72
   316.8 2087.09   353.4 2090.24   362.1 2092.62   423.2  2095.6   430.8 2099.26
#Mann= 4 ,-1,0
       0      .1       0   185.8    .045       0  201.31      .1       0
  320.05     .06       0
#XS Ineff= 2 , 0
                          248.45          2090.1
Permanent Ineff=
       F       F
Bank Sta=185.8,201.31
XS Rating Curve= 0 ,0
Exp/Cntr=0.3,0.1

Type RM Length L Ch R = 1 ,2718    ,133.7,138.2,143
XS GIS Cut Line= 4
2226691.81278663669304.5925324372226773.71295529669205.322493332
2226816.82248352 669110.572572692226872.72580399668957.324216307
#Sta/Elev= 30
       0 2095.44     6.9 2093.86    19.4 2092.88    28.3 2091.59    39.6 2089.18
    51.1 2085.54    65.2 2083.38    73.7 2084.11    82.2 2083.97   113.3 2081.59
   133.2 2080.88     142 2079.41   159.6 2080.15   177.2 2079.64     185 2077.82
   190.4 2077.51  200.512077.813   218.3 2080.29   231.2  2083.2   242.6 2081.67
   251.3 2081.41   255.2 2081.97   261.4 2084.26   264.6 2084.93   285.4 2084.85
   293.9 2086.02   323.7 2087.34     362 2090.73   387.6 2091.67   395.9 2092.71
#Mann= 4 ,-1,0
       0      .1       0     185    .045       0  200.51      .1       0
  242.79     .06       0
#XS Ineff= 2 , 0
           159.2  2082.4
Permanent Ineff=
       F       F
Bank Sta=185,200.51
XS Rating Curve= 0 ,0
Exp/Cntr(USF)=0,0
Exp/Cntr=0.3,0.1

Type RM Length L Ch R = 1 ,2580    ,63.5,60.5,58.1
XS GIS Cut Line= 5
2226743.64133687669362.5286282112226822.59601685 669280.16186386
2226856.49384651669254.1414425292226885.78868027669125.249310066
2226882.28739485669031.726200231
#Sta/Elev= 30
       0  2090.5    23.9 2087.31    29.6 2086.05    40.7 2082.51      47 2079.68
    52.8 2077.84    60.7 2078.32    90.5 2077.15   101.6 2077.53   111.7 2076.85
   121.1 2077.21   131.6 2075.28   136.3 2073.68   141.3 2073.29  147.192073.665
   156.4 2076.81     166 2077.57   173.4 2078.77   178.3 2078.48   190.6 2079.71
   197.5 2078.74   202.9  2078.5   223.4 2079.32   230.9 2080.26   252.2 2084.05
   256.3 2084.37   276.8 2084.43   317.1 2085.85   333.1 2085.88   382.6 2088.79
#Mann= 5 ,-1,0
       0     .06       0      90      .1       0   114.1     .06       0
   136.3    .045       0  147.19     .06       0
Bank Sta=136.3,147.19
XS Rating Curve= 0 ,0
Exp/Cntr(USF)=0,0
Exp/Cntr=0.3,0.1

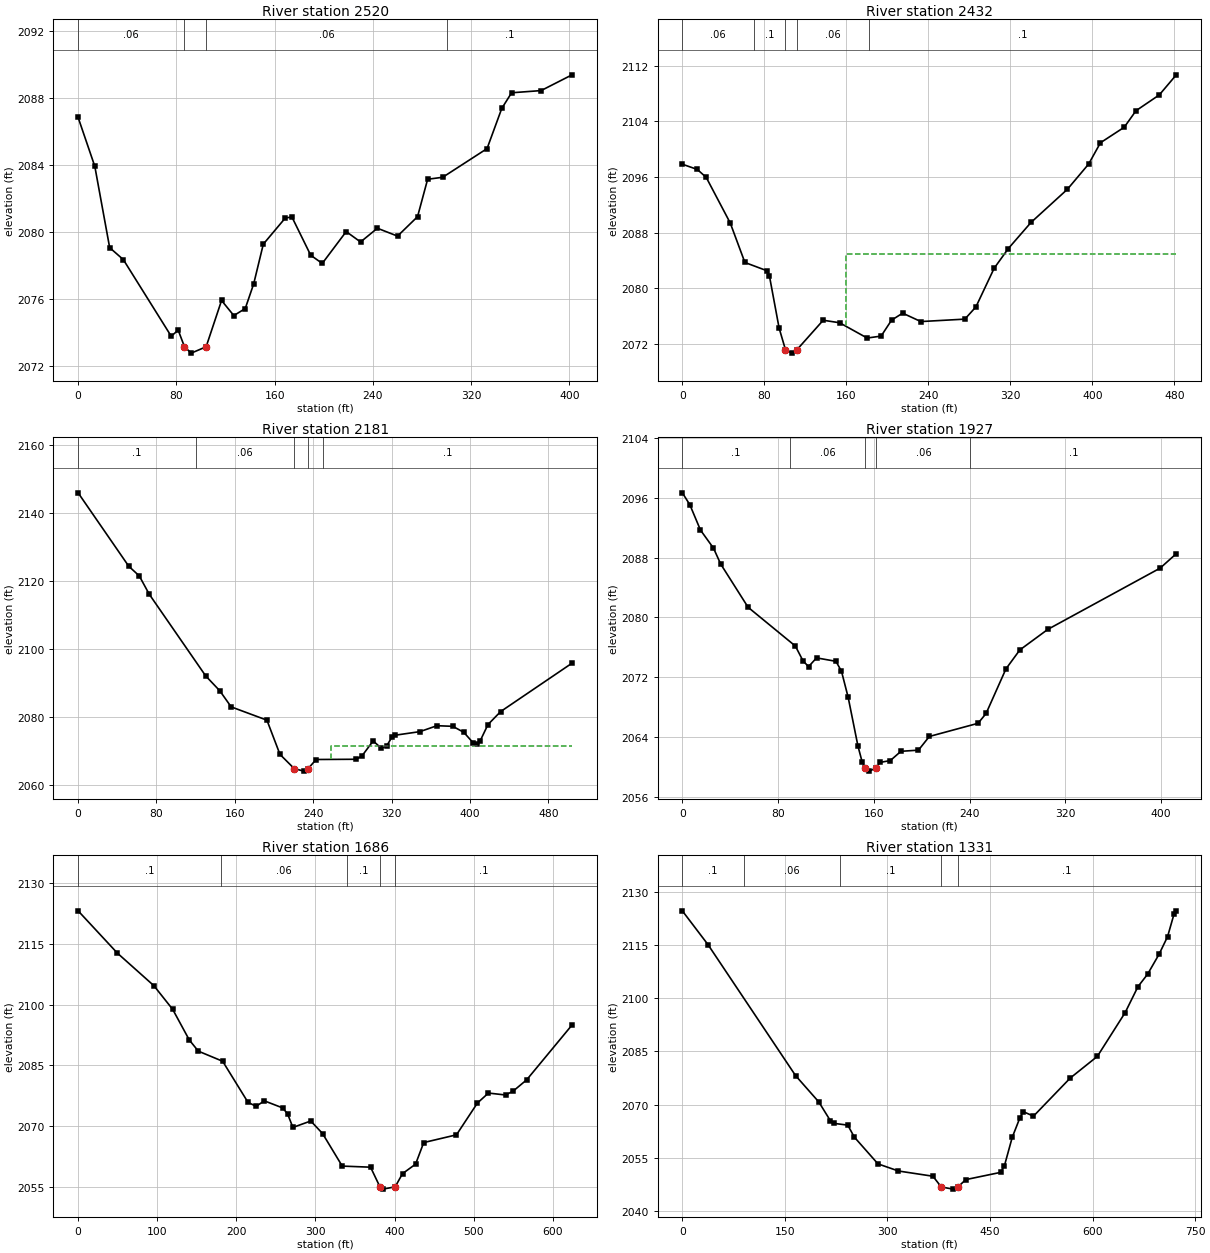
Type RM Length L Ch R = 1 ,2520    ,84.8,88.2,91
XS GIS Cut Line= 6
2226777.61815356669389.8644817582226830.24807493669339.475230945
2226864.30480898669307.1146920712226895.57639707669254.852034357
2226920.44711107669135.4726071812226923.28947838669035.989751201
#Sta/Elev= 30
       0 2086.85    13.6 2083.93    25.7 2079.08    36.8 2078.37    75.8  2073.8
    81.5 2074.16    86.6 2073.17    92.1 2072.79  104.242073.168   116.8 2075.93
   126.8 2075.03   136.1 2075.45     143 2076.93   150.8 2079.29   168.7 2080.85
   174.1 2080.91   189.4 2078.63   198.8 2078.14   218.3 2080.04     230 2079.42
   243.7 2080.24   260.1 2079.77   276.4 2080.93   284.6 2083.16   296.9 2083.28
     333 2084.99     345 2087.39     353 2088.32     377 2088.45   402.2 2089.39
#Mann= 4 ,-1,0
       0     .06       0    86.6    .045       0  104.24     .06       0
  300.75      .1       0
Bank Sta=86.6,104.24
XS Rating Curve= 0 ,0
Exp/Cntr(USF)=0,0
Exp/Cntr=0.3,0.1

Type RM Length L Ch R = 1 ,2432    ,251.4,250.7,248.6
XS GIS Cut Line= 3
2226769.09105161669462.3448482582226888.00396154669384.764375365
2227173.41780199669200.136463568
#Sta/Elev= 30
       0 2097.84    14.6 2097.09    23.3 2095.94    46.7 2089.39      61 2083.71
    82.7 2082.51    84.9  2081.8    94.4 2074.27  100.532071.186   107.1 2070.67
   111.9 2071.18   137.4  2075.4   153.4 2075.04   180.3 2072.84   193.9 2073.12
   204.1 2075.41   214.9 2076.42   232.7 2075.21   275.6 2075.56   286.4 2077.32
   304.2 2082.88     318 2085.71   340.1 2089.46   375.6 2094.23   396.4 2097.87
   407.9 2100.93   431.1 2103.16   442.6 2105.54   465.3 2107.81   481.9  2110.7
#Mann= 5 ,-1,0
       0     .06       0      70      .1       0  100.53    .045       0
   111.9     .06       0  181.98      .1       0
#XS Ineff= 2 , 0
                             160            2085
Permanent Ineff=
       F       F
Bank Sta=100.53,111.9
XS Rating Curve= 0 ,0
Exp/Cntr(USF)=0,0
Exp/Cntr=0.3,0.1

Type RM Length L Ch R = 1 ,2181    ,252.7,254.4,254.4
XS GIS Cut Line= 3
2226820.28867068669733.9498770322226978.35830085669628.183446915
2227203.44391757669409.366123241
#Sta/Elev= 30
       0 2145.93    51.7 2124.33    62.4  2121.5    72.6  2116.1   130.2 2092.08
   144.6  2087.7   156.2 2082.97   192.7 2079.06     206    2069   220.6  2064.8
   230.4 2064.07   234.7 2064.79   242.9 2067.49   284.1 2067.56   289.8 2068.58
   301.1 2072.94   309.6 2070.79     315 2071.55   320.7 2074.24   323.7 2074.64
   348.9 2075.69   366.2 2077.43   382.4 2077.25   393.6 2075.49   402.9 2072.49
   406.8 2072.08   410.3 2072.95   418.3 2077.77   431.2 2081.58   504.1 2095.83
#Mann= 5 ,-1,0
       0      .1       0     120     .06       0   220.6    .045       0
   234.7     .06       0  250.19      .1       0
#XS Ineff= 2 , 0
                           258.6         2071.54
Permanent Ineff=
       F       F
Bank Sta=220.6,234.7
XS Rating Curve= 0 ,0
Exp/Cntr=0.3,0.1

Type RM Length L Ch R = 1 ,1927    ,241,240.6,239.1
XS GIS Cut Line= 3
 2227012.3167201669837.919156501 2227213.3548784669724.889119002
2227308.26559691669569.580670529
#Sta/Elev= 30
       0 2096.65     6.3 2095.04    15.1 2091.68      26 2089.26      32 2087.14
    54.9 2081.36    94.4 2076.18   100.8  2074.2   105.4 2073.43   112.1  2074.6
   128.3 2074.14   132.9 2072.82   138.5 2069.33   146.7  2062.8   150.2 2060.69
  152.882059.864   155.9 2059.47     162 2059.87     165 2060.63   173.7 2060.88
   182.6 2062.12   197.2 2062.27   206.3  2064.1     247 2065.86   253.7 2067.17
   270.3 2073.13   281.9 2075.66   305.3 2078.41   399.1 2086.59   412.6 2088.52
#Mann= 5 ,-1,0
       0      .1       0      90     .06       0  152.88    .045       0
     162     .06       0  240.63      .1       0
Bank Sta=152.88,162
XS Rating Curve= 0 ,0
Exp/Cntr(USF)=0,0
Exp/Cntr=0.3,0.1

Type RM Length L Ch R = 1 ,1686    ,352.2,354.8,355.4
XS GIS Cut Line= 2
 2227100.4583639670187.3259825562227495.92464607669704.064152145
#Sta/Elev= 30
       0 2123.12    49.6  2112.7    95.8 2104.66   119.6 2098.81   140.6 2091.26
     152 2088.52   182.7 2086.03   214.7 2075.92     225 2074.91   235.4 2076.27
   258.5 2074.53   264.8 2073.06   271.5 2069.71   294.1  2071.3     309 2068.21
   333.9 2060.18   369.7 2059.91  381.542055.064   385.3  2054.5   400.8 2055.07
   410.1 2058.32   426.6 2060.66   436.9 2065.98   478.3 2067.89   504.8 2075.73
   518.7 2078.19   540.3 2077.71   549.9 2078.66     567 2081.44   624.4 2094.97
#Mann= 5 ,-1,0
       0      .1       0     180     .06       0     340      .1       0
  381.54    .045       0   400.8      .1       0
Bank Sta=381.54,400.8
XS Rating Curve= 0 ,0
Exp/Cntr(USF)=0,0
Exp/Cntr=0.3,0.1

Type RM Length L Ch R = 1 ,1331    ,171.2,178.6,180.6
XS GIS Cut Line= 3
2227347.81940091670363.0200028982227768.42673177669960.436670055
2227870.74320239669864.424068866
#Sta/Elev= 30
       0 2124.57    37.4  2115.1   165.6 2078.21   199.6 2070.79   216.4 2065.55
     222 2064.76     242 2064.27   251.4 2060.93   286.1 2053.37   316.1 2051.36
   366.5 2049.89   378.7 2046.87     396 2046.26  402.982046.864   414.6 2048.94
   465.6 2050.98   471.2 2052.91   482.5 2060.83   493.8 2066.36   498.8 2068.05
   513.6  2066.8   567.4 2077.53     607 2083.62   647.7 2095.95   666.4 2103.24
   680.6 2106.78   697.1  2112.3   709.7  2117.3     719 2123.57   722.5 2124.59
#Mann= 5 ,-1,0
       0      .1       0      90     .06       0     230      .1       0
   378.7    .045       0  402.98      .1       0
Bank Sta=378.7,402.98
XS Rating Curve= 0 ,0
Exp/Cntr=0.3,0.1

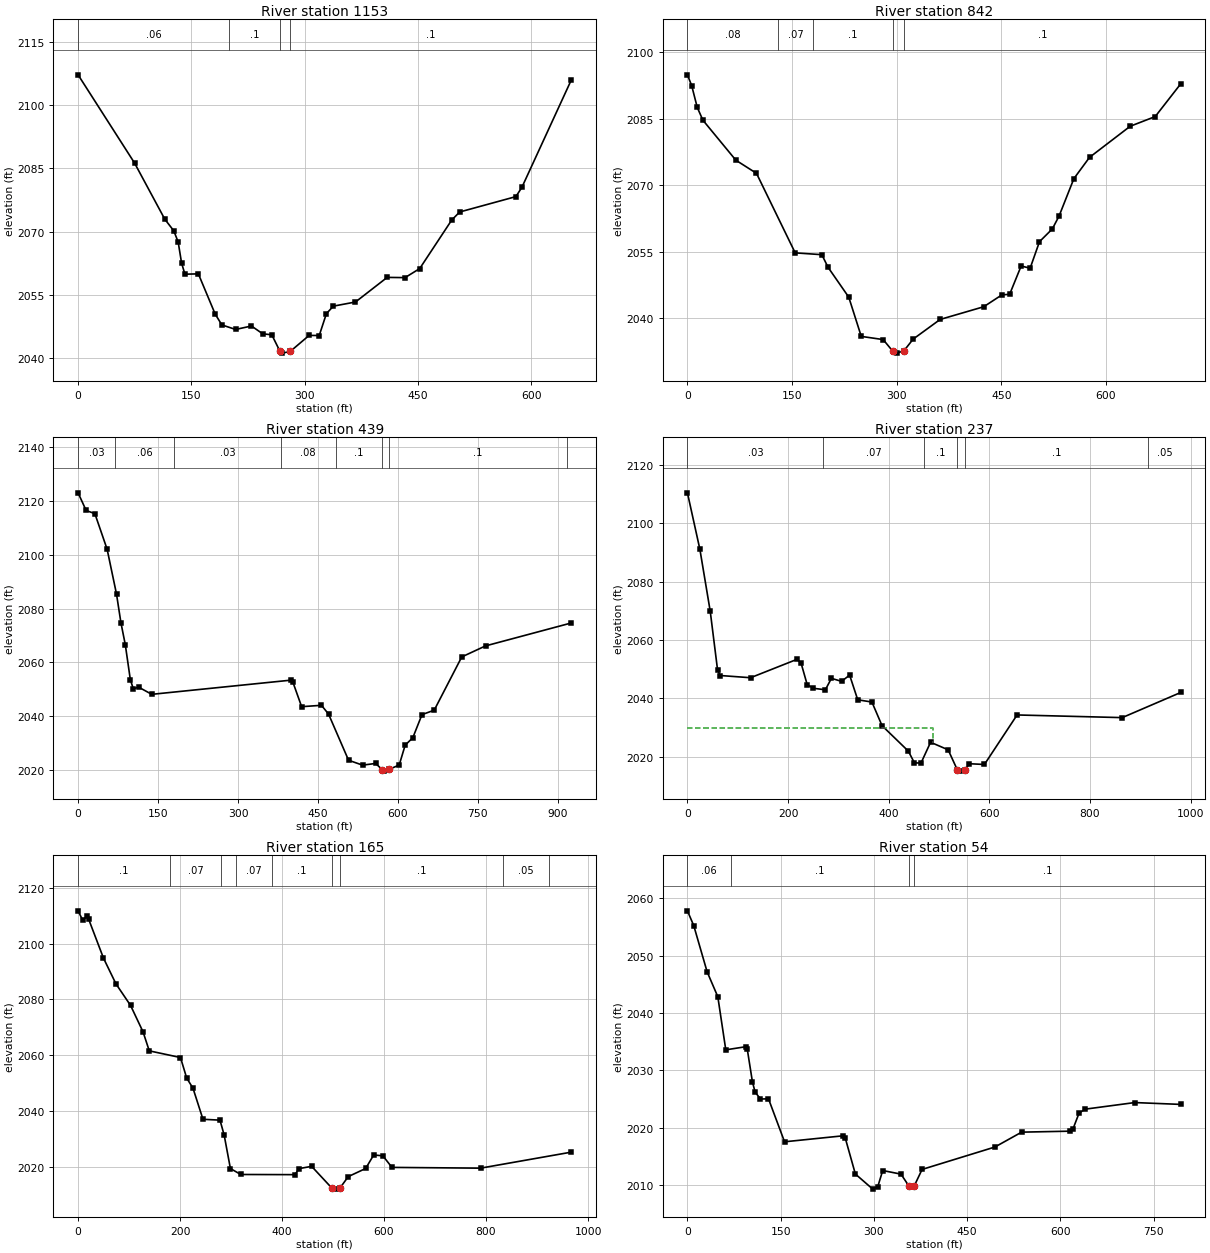
Type RM Length L Ch R = 1 ,1153    ,313.1,310.7,302.7
XS GIS Cut Line= 3
2227436.87061858670372.3712661132227814.91204826670189.423505969
2227982.67742167670027.731087253
#Sta/Elev= 30
       0 2107.12    74.8 2086.23   114.8 2072.95   126.7  2070.2   132.5 2067.54
     137 2062.57   141.4 2059.94   159.2 2060.02   181.5 2050.49   190.3 2047.94
   208.5 2046.86   229.5 2047.68   244.4 2045.83   256.4  2045.6  267.212041.698
   270.3 2041.26   280.82041.655   305.8 2045.45   319.2 2045.43   328.7 2050.61
   337.9 2052.38   367.2 2053.36   409.1 2059.18   432.8 2059.13   452.2 2061.27
   494.6 2072.76   505.1 2074.66   579.5  2078.3   587.5 2080.51     653 2105.97
#Mann= 4 ,-1,0
       0     .06       0     200      .1       0  267.21    .045       0
   280.8      .1       0
Bank Sta=267.21,280.8
XS Rating Curve= 0 ,0
Exp/Cntr(USF)=0,0
Exp/Cntr=0.3,0.1

Type RM Length L Ch R = 1 ,842     ,400.8,403.2,407.1
XS GIS Cut Line= 3
2227630.17108166670601.5647561332227816.65931631670575.514012604
2228050.90793046670112.513988845
#Sta/Elev= 30
       0 2094.93     6.1  2092.5    14.1 2087.57    22.2 2084.68    69.4 2075.65
      99 2072.68   154.5 2054.71   192.7  2054.3   201.6 2051.45   231.3  2044.7
   249.2 2035.84   280.6 2035.12     294 2032.57   299.8 2032.06  310.31 2032.57
   323.6 2035.23   362.3 2039.67   424.8 2042.54   450.9 2045.23   461.9 2045.34
   478.4 2051.74   491.3 2051.25   504.7 2057.24   523.1 2060.12   532.8 2063.04
     554 2071.48   576.4 2076.28   634.7 2083.31   670.6  2085.5   707.2  2092.9
#Mann= 5 ,-1,0
       0     .08       0     130     .07       0     180      .1       0
     294    .045       0  310.31      .1       0
Bank Sta=294,310.31
XS Rating Curve= 0 ,0
Exp/Cntr(USF)=0,0
Exp/Cntr=0.3,0.1

Type RM Length L Ch R = 1 ,439     ,200.1,201.5,202.7
XS GIS Cut Line= 4
2227638.43716946670877.8555633812228087.10853462670761.054575115
 2228358.7385371670568.2505341462228451.55276505670479.249928816
#Sta/Elev= 30
       0  2122.9    15.1 2116.35    31.5 2115.18    54.5 2101.95    72.1 2085.32
    80.3 2074.79    88.6 2066.53      98 2053.63   103.6  2050.2   113.4 2050.86
   138.2 2048.17   398.8 2053.42   402.7  2052.8   419.3 2043.59   456.5  2044.1
   469.8 2040.84   507.3 2023.73   533.6 2021.91   558.1 2022.54   570.4 2020.25
   573.3 2019.69   582.7  2020.3   602.3 2021.95   613.5 2029.34   627.8 2032.06
     645 2040.64     668  2042.3   719.6 2062.04   764.2 2066.13   925.3 2074.65
#Mann= 8 ,-1,0
       0     .03       0      70     .06       0     180     .03       0
     380     .08       0  483.63      .1       0   570.4    .045       0
   582.7      .1       0  916.73     .05       0
Bank Sta=570.4,582.7
XS Rating Curve= 0 ,0
Exp/Cntr=0.3,0.1

Type RM Length L Ch R = 1 ,237     ,72.2,71.7,71.5
XS GIS Cut Line= 4
2227739.47520966670930.3112859062228251.66351842670876.971684909
2228370.62905745670822.355015349 2228649.1810542 670636.89054813
#Sta/Elev= 30
       0 2110.36    24.8 2091.01    45.4 2069.76    59.9 2049.77      65 2047.85
   125.5 2047.09   217.9 2053.39   225.9 2052.09     238 2044.76     250 2043.48
   274.2 2042.97   286.2 2046.88   306.3 2045.85   322.4 2047.98   338.5 2039.54
   366.7 2038.77   386.8 2030.69   439.1 2021.97   451.1 2017.97   464.2 2017.88
   483.3 2025.01   518.2 2022.42   536.3 2015.62   541.9 2015.13  551.892015.621
   560.4 2017.66   590.3 2017.41   655.2 2034.35   864.2 2033.44   980.5 2042.05
#Mann= 6 ,-1,0
       0     .03       0     270     .07       0     470      .1       0
   536.3    .045       0  551.89      .1       0  915.86     .05       0
#XS Ineff= 2 , 0
         488.275    2030
Permanent Ineff=
       T       F
Bank Sta=536.3,551.89
XS Rating Curve= 0 ,0
Exp/Cntr(USF)=0,0
Exp/Cntr=0.3,0.1

Type RM Length L Ch R = 1 ,165     ,110.4,110.7,110.6
XS GIS Cut Line= 4
2227827.33833677671036.8979836712228275.51508674670946.451101497
2228395.63263391670883.8753228712228732.22332704670719.096827831
#Sta/Elev= 30
       0 2111.79       9 2108.42    17.2 2109.86    20.8 2108.76    49.8 2094.83
    74.3 2085.59   102.9 2077.87   127.4 2068.38   139.6 2061.58   200.8 2059.19
     213 2051.81   225.3  2048.2   244.9 2037.04   278.3 2036.74   286.5 2031.34
   298.7 2019.38   319.1 2017.25   425.2 2017.19   433.4 2019.36     458 2020.17
   497.2 2012.46   507.6    2012  513.872012.471   529.8 2016.49   563.9  2019.4
   579.7 2024.25   597.7 2023.94   615.5 2019.79   789.2 2019.52   967.4 2025.27
#Mann= 9 ,-1,0
       0      .1       0     180     .07       0     280      .1       0
     310     .07       0     380      .1       0   497.2    .045       0
  513.87      .1       0  832.65     .05       0  922.65      .1       0
Bank Sta=497.2,513.87
XS Rating Curve= 0 ,0
Exp/Cntr(USF)=0,0
Exp/Cntr=0.3,0.1

Type RM Length L Ch R = 1 ,54      ,,,
XS GIS Cut Line= 5
2228034.62507075671113.8056590612228260.89338971  671025.9531342
2228336.04874294671030.5390230872228426.13387542670999.407546112
2228738.61651898670783.006653587
#Sta/Elev= 30
       0 2057.79    10.2 2055.21    31.7 2047.17    48.9 2042.83    61.7 2033.59
    94.4 2034.14    96.1 2033.82   104.6 2027.98   108.9 2026.24   117.5 2025.03
   130.4 2025.06   156.2 2017.58     250 2018.62     254 2018.18   270.1 2011.97
   298.1 2009.34   306.1 2009.76   314.1 2012.58   343.5 2011.95356.22052009.868
364.61992009.859   377.4 2012.77   494.5 2016.67   537.5 2019.26   615.3 2019.43
   620.2 2019.85   629.9 2022.58   639.6 2023.26   719.4 2024.41   793.4 2024.09
#Mann= 4 ,-1,0
       0     .06       0      70      .1       0356.2205    .045       0
364.6199      .1       0
Bank Sta=356.2205,364.6199
XS Rating Curve= 0 ,0
Exp/Cntr(USF)=0,0
Exp/Cntr=0.3,0.1
LCMann Table=0

Chan Stop Cuts=-1
Use User Specified Reach Order=0
Composite Channel Slope=5